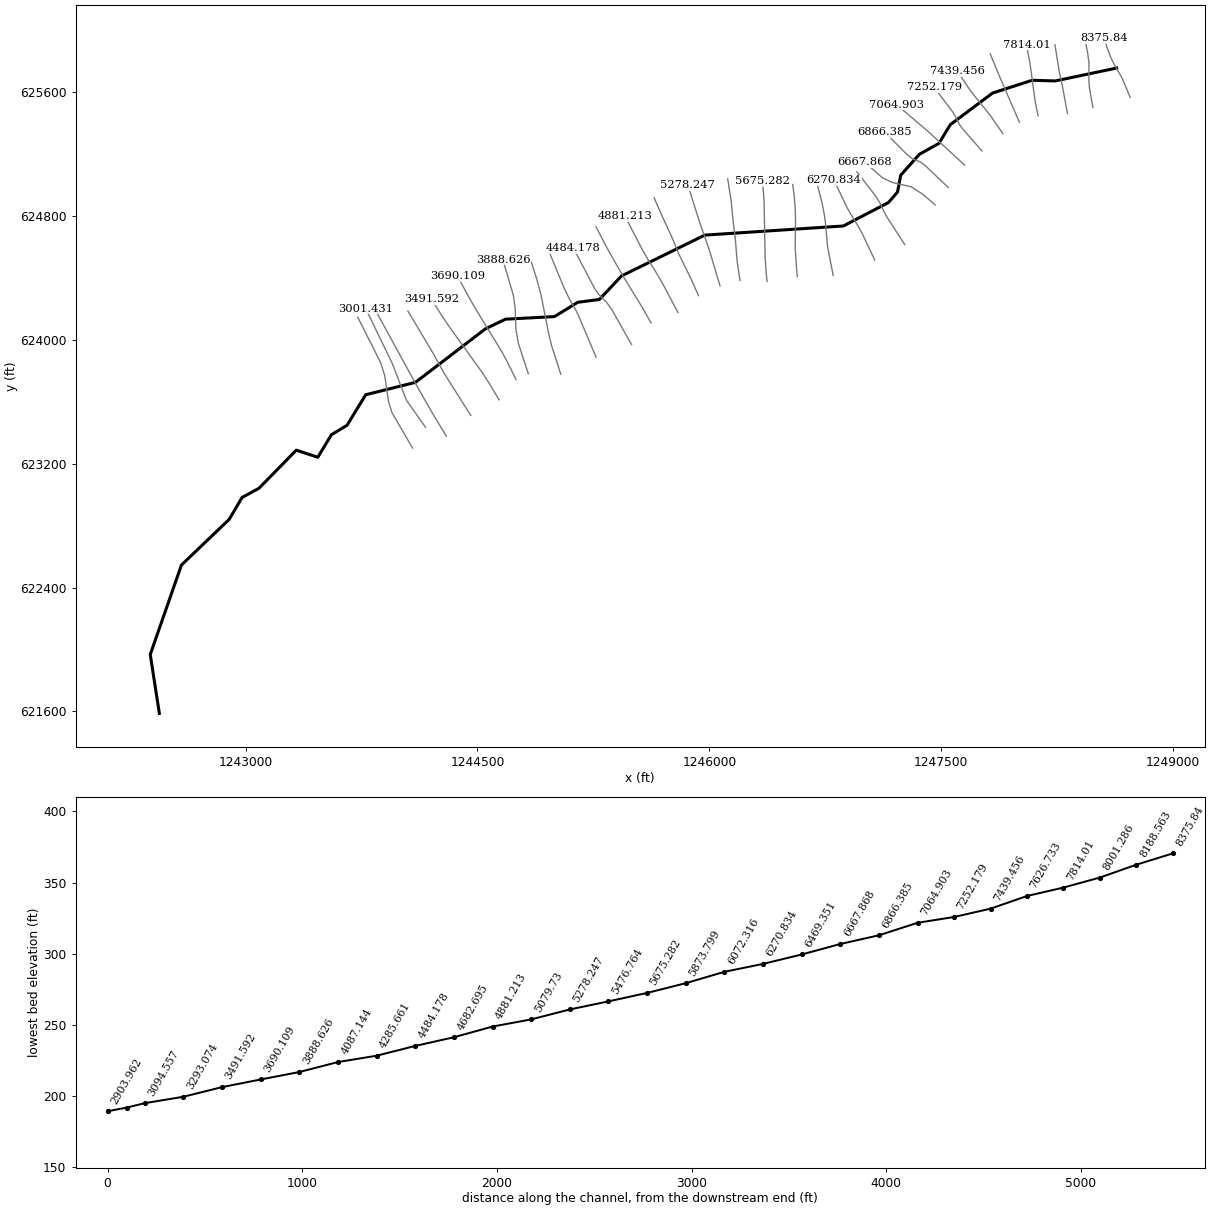
--- 400_ras.prj (project) ---

Proj Title=400
Current Plan=p01
Default Exp/Contr=0.3,0.1
English Units
Geom File=g01
Flow File=f01
Plan File=p01
Y Axis Title=Elevation
X Axis Title(PF)=Main Channel Distance
X Axis Title(XS)=Station
BEGIN DESCRIPTION:
RFD model 400 exported to HEC-RAS
END DESCRIPTION:

--- 400_ras.p01 (plan) ---

Plan Title=Plan 01
Program Version=4.10
Short Identifier=Plan 01
Geom File=g01
Flow File=f01
Subcritical Flow
Calc Critical at every XS
Secant Critical Depth

--- 400_ras.f01 (steady flow) ---

Flow Title=Flow 01
Program Version=5.01
Number of Profiles= 5
Profile Names=10yr,25yr,50yr,100yr,500yr
River Rch & RM=400,46, 8375.84
  380.83  453.77  540.83  576.19  674.65
River Rch & RM=400,46,8188.563
  391.35  468.16  558.49   597.4  703.11
River Rch & RM=400,46,8001.286
  408.77  492.13  587.93  632.97  751.14
River Rch & RM=400,46, 7814.01
  419.01  506.29  605.34   654.1  779.87
River Rch & RM=400,46,7626.733
  431.11  523.08  626.01  679.28  814.29
River Rch & RM=400,46,7439.456
  444.83  542.21  649.58  708.13  853.93
River Rch & RM=400,46,7252.179
  459.95  563.38  675.69  740.25  898.34
River Rch & RM=400,46,7064.903
  464.61  569.92  683.76  750.21  912.17
River Rch & RM=400,46,6866.385
  484.41  597.85  718.26  792.95  971.79
River Rch & RM=400,46,6667.868
  485.65   599.6  720.42  795.63  975.56
River Rch & RM=400,46,6469.351
  498.93  618.43  743.72  824.64 1016.32
River Rch & RM=400,46,6270.834
  511.12  635.78   765.2   851.5 1054.23
River Rch & RM=400,46,6072.316
  519.57  647.84  780.13  870.22 1080.76
River Rch & RM=400,46,5873.799
  523.98  654.15  787.96  880.05 1094.73
River Rch & RM=400,46,5675.282
  565.83  714.38   862.7  974.54 1230.07
River Rch & RM=400,46,5476.764
  575.46  728.33  880.04  996.61 1261.96
River Rch & RM=400,46,5278.247
  593.11  753.98  911.95 1037.37 1321.12
River Rch & RM=400,46, 5079.73
  600.75  765.12  925.81 1055.14 1347.02
River Rch & RM=400,46,4881.213
  614.73  785.57  951.29 1087.87 1394.89
River Rch & RM=400,46,4682.695
  617.73  789.96  956.76 1094.92 1405.21
River Rch & RM=400,46,4484.178
  627.42  804.18  974.48 1117.77 1438.78
River Rch & RM=400,46,4285.661
  632.39  811.48  983.58 1129.53 1456.09
River Rch & RM=400,46,4087.144
  644.15   828.8 1005.19 1157.49 1497.37
River Rch & RM=400,46,3888.626
   650.1  837.59 1016.16 1171.71 1518.42
River Rch & RM=400,46,3690.109
  654.81  844.54 1024.84 1182.98 1535.12
River Rch & RM=400,46,3491.592
     669  865.55 1051.08 1217.13 1585.87
River Rch & RM=400,46,3293.074
  673.13  871.68 1058.74 1227.11 1600.75
River Rch & RM=400,46,3094.557
  683.84  887.59 1078.63 1253.09 1639.53
River Rch & RM=400,46,3001.431
  687.11  892.46 1084.72 1261.05 1651.45
River Rch & RM=400,46,2903.962
  688.55  894.61 1087.41 1264.58 1656.72
River Rch & RM=400,46, 2761.98
  691.43   898.9 1092.78  1271.6 1667.24
River Rch & RM=400,46,2502.346
  696.07  905.82 1101.43 1282.94 1684.24
Boundary for River Rch & Prof#=400,46,1
Up Type= 0
Dn Type= 2
Boundary for River Rch & Prof#=400,46,2
Up Type= 0
Dn Type= 2
Boundary for River Rch & Prof#=400,46,2
Up Type= 0
Dn Type= 2
Boundary for River Rch & Prof#=400,46,2
Up Type= 0
Dn Type= 2
Boundary for River Rch & Prof#=400,46,2
Up Type= 0
Dn Type= 2

--- 400_ras.g01 (geometry) ---

Geom Title=400
Program Version=4.10

River Reach=400,46
Reach XY= 30
1248634.47630695625758.0080876951248237.80975491625674.674790651
1248087.80979931625678.8414604811247831.97653902  625596.3414924
1247558.64328042625392.1748943181247485.30996522625271.341599017
1247358.64333382 625200.508290411247237.81003219625065.508333996
1247216.97670186624956.3417003451247158.64338371624888.841722101
1246866.97679871 624737.175108911245970.31039485624678.008485928
1245431.14387962624413.8419134171245288.64391729624262.175295919
1245148.64395803624243.8419721421244997.81066656624151.342003956
1244681.14409277624134.6753514711244551.14412934624072.175373808
1244098.64425278623726.3421563211243776.97767869623646.342189431
1243656.14437523623448.8422515541243555.31106991623388.008939266
1243466.97775838623242.175651789 1243327.8111341623288.008975565
1243086.14453158623041.3423891811242976.97789538622982.175743252
1242893.64458251 622840.509121061242584.91917637622545.495342836
1242383.25255236 621967.162187071242442.07692057621586.680412546

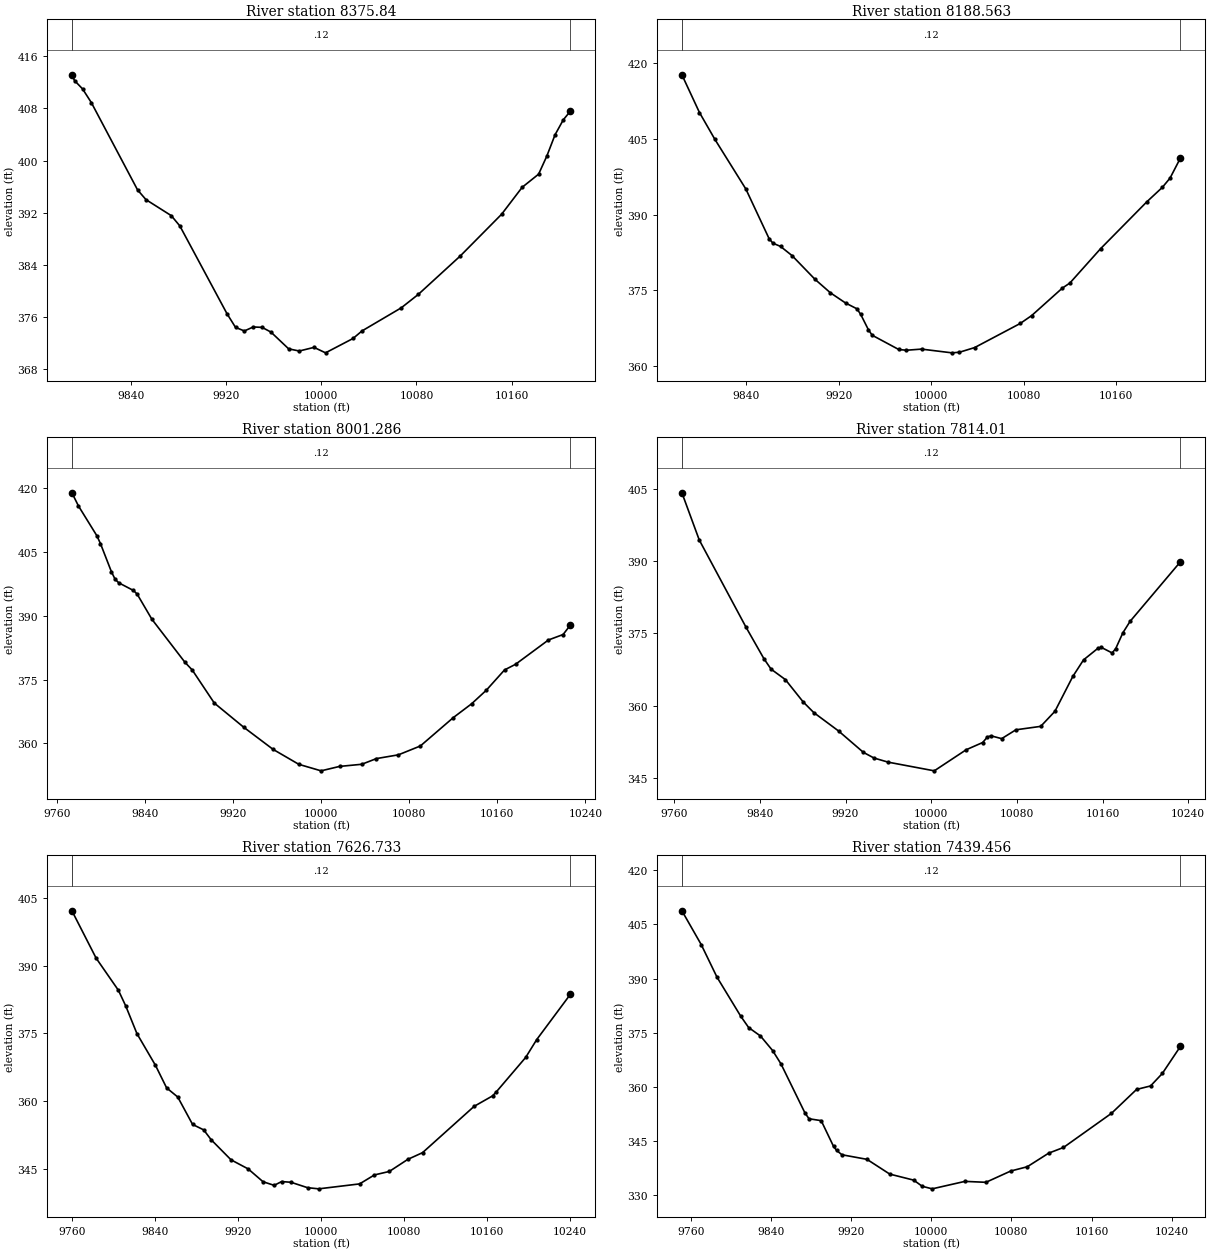
Type RM Length L Ch R = 1 , 8375.84,187.276700,187.276700,187.276700
XS GIS Cut Line= 6
1248722.20651985625568.2030324711248669.39473308625694.439183053
1248617.17315985625784.2333763231248598.86220794625821.286902923
1248578.67456952625872.8592348121248553.38159921625950.013710432
#Sta/Elev= 30
9790.635413.16099792.836412.27129799.598410.9918 9806.96408.89199845.801395.4894
9852.863394.00359874.062391.55399881.258389.97889920.836376.51979928.049374.4068
9935.476 373.8619942.903374.47169950.331374.41279957.758373.69089972.666371.1158
9981.575 370.7849993.956371.341410003.64370.503310026.73372.706610034.28373.8651
10067.22377.408210081.52379.464610116.75385.356210151.51391.767410168.77395.8994
10182.58397.916210189.49400.693910196.39403.9584 10203.3406.250810209.35 407.603
#Mann= 3 , 0 , 0
9790.635    0.12       09790.635    0.12       010209.35    0.12       0
#XS Ineff= 2 , 0
       0                               0
Bank Sta=9790.635,10209.35
Exp/Cntr=0.3,0.1

Type RM Length L Ch R = 1 ,8188.563,187.276800,187.276800,187.276800
XS GIS Cut Line= 6
1248481.04842155625502.862092648 1248458.5208443 625628.75361364
1248454.74720503 625678.621492561248455.63014433625789.128393766
 1248446.7445442625856.6398662551248432.40918588625930.156143391
#Sta/Elev= 30
9784.234417.72639799.422410.24279812.806404.90549839.574395.07089859.647 385.248
9862.964  384.329869.598383.67919879.549381.86039899.451377.14869912.714374.4858
9925.875372.45579935.746371.29899939.036370.17549945.616367.16549948.907366.0615
9971.915363.23069978.481363.08279991.611363.308310017.89362.567910024.46362.6873
10037.59  363.6110077.03  368.3910086.95369.956810113.43375.393710120.04376.4159
10146.57383.216210186.69392.539710200.06395.392310206.74397.233410215.77 401.238
#Mann= 3 , 0 , 0
9784.234    0.12       09784.234    0.12       010215.77    0.12       0
#XS Ineff= 2 , 0
       0                               0
Bank Sta=9784.234,10215.77
Exp/Cntr=0.3,0.1

Type RM Length L Ch R = 1 ,8001.286,187.276700,187.276700,187.276700
XS GIS Cut Line= 6
1248316.63495032625462.7285156531248280.69203603625657.250401184
1248274.52590341625684.2252123841248273.97158216625686.146859583
1248265.30391279625725.7180296451248235.27560341625908.240125507
#Sta/Elev= 30
9773.515418.96779779.427415.88119796.108408.88939799.445407.01989809.454400.3607
 9812.79   398.69816.127397.77199829.472395.97239832.808395.11529846.154389.2175
9876.181379.08769882.854377.26389902.872369.48519929.563363.80449956.254 358.592
9979.681355.06559999.886353.5345 10016.7354.575610036.85355.0785 10050.2  356.42
10070.15357.3011 10090.1359.385410120.02366.061210136.64 369.30910149.94372.4831
10166.57377.280310176.54378.602510206.47  384.3310219.77385.610710226.49387.8734
#Mann= 3 , 0 , 0
9773.515    0.12       09773.515    0.12       010226.49    0.12       0
#XS Ineff= 2 , 0
       0                               0
Bank Sta=9773.515,10226.49
Exp/Cntr=0.3,0.1

Type RM Length L Ch R = 1 , 7814.01,187.276700,187.276700,187.276700
XS GIS Cut Line= 6
1248127.14322601625449.4815810751248116.70107253625493.862280951
1248105.83496608625551.8756178841248088.98675425625679.946009041
1248073.08036837625792.7476266261248051.05707125625908.544318428
#Sta/Elev= 30
9767.209404.1717 9783.42394.37369827.096376.26839843.785369.74789850.461367.5772
9863.813365.41069880.428360.78069890.356358.56179913.522354.74099936.688350.3076
9946.616349.12999959.854 348.27310002.87346.474210032.69350.851710048.09352.3535
10052.57353.519610055.88353.737910065.82353.154610079.07 354.98710102.27355.7042
10115.53358.823410132.22366.050810142.24369.4932 10155.6371.888210158.94372.0778
10168.96 370.939 10172.3371.833310178.98375.106910185.66377.471910232.79389.8668
#Mann= 3 , 0 , 0
9767.209    0.12       09767.209    0.12       010232.79    0.12       0
#XS Ineff= 2 , 0
       0                               0
Bank Sta=9767.209,10232.79
Exp/Cntr=0.3,0.1

Type RM Length L Ch R = 1 ,7626.733,187.276800,187.276800,187.276800
XS GIS Cut Line= 5
1248005.56903687625407.7423840941247910.46057756625627.309338666
1247909.66312539625629.1434788031247881.32560622625693.640694821
1247816.72225323625849.631101605
#Sta/Elev= 30
9759.719402.12049783.073391.62759804.525384.51929811.676381.00739822.402374.9178
9840.279367.88839851.006362.90229861.732360.88189876.033354.8106 9886.76353.6012
 9893.91351.42959913.069 346.9759929.577344.96659943.966342.11799954.692341.3217
9961.843342.15619970.848342.00629986.871340.80349997.597340.548110037.01341.6412
10051.34 343.62910065.68344.400110083.49347.076410097.69348.5594 10147.4 358.812
10165.16361.130510168.71361.999610197.12369.653810207.77  373.6110240.29383.6559
#Mann= 3 , 0 , 0
9759.719    0.12       09759.719    0.12       010240.29    0.12       0
#XS Ineff= 2 , 0
       0                               0
Bank Sta=9759.719,10240.29
Exp/Cntr=0.3,0.1

Type RM Length L Ch R = 1 ,7439.456,187.276700,187.276700,187.276700
XS GIS Cut Line= 6
1247898.38967437625334.4364400211247817.35179658 625451.83904225
1247721.84203279625569.5399397661247686.67758994625615.700905122
1247644.11854993625677.1439325821247605.89877474625736.417277052
#Sta/Elev= 30
9751.215408.79769770.453399.43649786.237390.37429809.913379.55039817.805376.3973
9829.642374.04889841.756370.01129850.059366.32379874.065352.67129878.103351.0834
9890.219350.56299902.591343.38949905.675342.28379910.914341.09669935.882339.8271
9958.648335.73039982.507334.05769991.053332.3475   10001  331.6410033.64333.7087
10054.62333.451710079.37336.583210095.87337.767610117.23341.538610132.03343.1217
10179.89352.586610204.94359.220510218.92360.193610230.64363.648210248.78371.1921
#Mann= 3 , 0 , 0
9751.215    0.12       09751.215    0.12       010248.78    0.12       0
#XS Ineff= 2 , 0
       0                               0
Bank Sta=9751.215,10248.78
Exp/Cntr=0.3,0.1

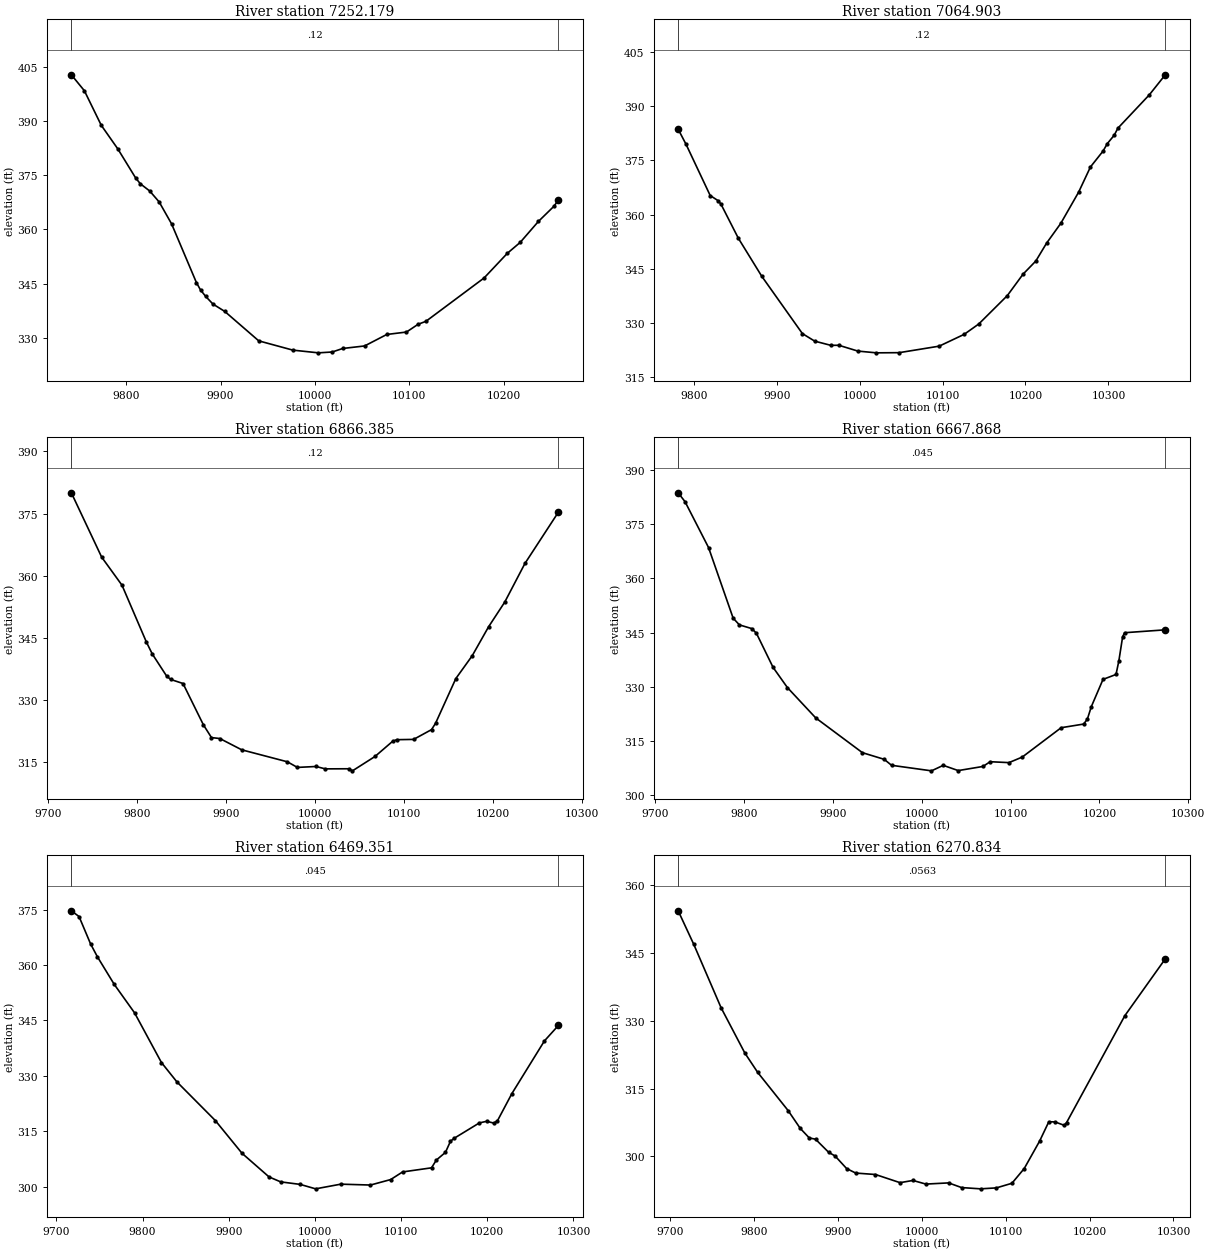
Type RM Length L Ch R = 1 ,7252.179,187.276700,187.276700,187.276700
XS GIS Cut Line= 6
1247763.49243984625221.6956137471247633.38008758625370.727535293
1247615.64930771625396.9275448661247591.26168155625446.025828619
1247570.28387272625479.7155059391247454.28027788625633.113060394
#Sta/Elev= 30
9741.842402.9025 9755.66398.47569773.577388.88729791.113382.34099810.071 374.258
9815.017372.6645 9824.91370.66989834.952367.62659848.104361.55069874.407345.2756
9878.791343.21159884.267341.42829891.943339.31069904.441337.27229940.489329.1047
9976.646326.531510003.73325.781410018.35326.012710029.49326.992210052.68327.6892
 10076.2 330.87710097.08331.550410109.42333.707210117.65334.514510179.35346.5504
10204.03353.398610217.62356.414710236.94362.234510253.39366.435410258.17368.1875
#Mann= 3 , 0 , 0
9741.842    0.12       09741.842    0.12       010258.17    0.12       0
#XS Ineff= 2 , 0
       0                               0
Bank Sta=9741.842,10258.17
Exp/Cntr=0.3,0.1

Type RM Length L Ch R = 1 ,7064.903,198.517300,198.517300,198.517300
XS GIS Cut Line= 3
1247651.33003864 625130.716656641247410.94417685625351.761127263
1247212.00415331625520.307536125
#Sta/Elev= 30
9781.275383.6366 9790.82379.43989819.902365.27129829.597363.82599833.004362.8352
9853.832353.44429882.032342.92559931.059327.04059945.926324.94849965.314323.7896
9975.008323.80459997.915322.1987 10020.2321.711510047.71321.759410095.97323.5606
10126.09326.829510143.69329.695910178.09337.546510197.14343.505810212.49347.1331
10225.39352.059310242.59357.563110264.09366.200210278.35373.180410293.58377.5881
10298.65379.630610307.09381.993410311.39383.907210349.41393.172410368.58 398.708
#Mann= 3 , 0 , 0
9781.275    0.12       09781.275    0.12       010368.58    0.12       0
#XS Ineff= 2 , 0
       0                               0
Bank Sta=9781.275,10368.58
Exp/Cntr=0.3,0.1

Type RM Length L Ch R = 1 ,6866.385,198.517300,198.517300,198.517300
XS GIS Cut Line= 6
1247545.84510778624985.3818789291247391.25682084 625132.08426251
1247359.31096937625153.5073407011247314.83539757625171.069039183
1247278.92428936625198.3792027271247136.36353795625341.605029155
#Sta/Elev= 30
9726.573380.03029760.617364.50149783.452357.72049810.854343.99839817.443341.1277
9833.688335.75039838.255334.97199851.956334.00199874.791324.0435 9883.91320.9492
9893.297320.72319917.866317.99829969.128315.10739980.339 313.753 10001.3313.9749
10011.65313.401110038.21313.426110042.18312.925610067.47316.389910087.14320.0284
10091.88320.442410110.81320.512110130.92322.869510135.47324.404510158.23335.1961
10176.59340.692510195.02347.699610213.14353.6497 10235.8362.972510273.44  375.38
#Mann= 3 , 0 , 0
9726.573    0.12       09726.573    0.12       010273.44    0.12       0
#XS Ineff= 2 , 0
       0                               0
Bank Sta=9726.573,10273.44
Exp/Cntr=0.3,0.1

Type RM Length L Ch R = 1 ,6667.868,198.517300,198.517300,198.517300
XS GIS Cut Line= 6
1247461.55628675624872.9328742761247378.82947201624943.428783137
1247307.00224722624989.7716606181247181.35778539625018.892026194
1247121.45632936625047.6032896071247002.30668337625150.169662375
#Sta/Elev= 30
9725.837383.61719733.602381.14389760.027368.49779787.744348.97379794.764347.1197
9808.681346.09849813.915344.81729832.661335.38669848.767 329.8129880.688321.4192
9933.242311.81349957.765309.97279966.062308.3249   10011306.794310024.23308.3109
10041.09 306.86410068.92308.003910077.04309.314910098.21 309.06410113.18310.6009
10156.96318.709910182.27319.715610186.49321.103410190.89324.510610204.08332.0608
10218.71333.420610221.92337.186710226.15343.815410228.34344.954710274.17 345.751
#Mann= 3 , 0 , 0
9725.837   0.045       09725.837   0.045       010274.17   0.045       0
#XS Ineff= 2 , 0
       0                               0
Bank Sta=9725.837,10274.17
Exp/Cntr=0.3,0.1

Type RM Length L Ch R = 1 ,6469.351,198.517200,198.517200,198.517200
XS GIS Cut Line= 6
1247263.84166448624616.5547062181247152.96397993 624788.21834119
1247126.51014568624835.8429971851247105.85136694624881.236694198
 1247078.1368784624927.3386103031246954.20699365625087.595542753
#Sta/Elev= 30
9717.409374.71359726.367373.14719739.734365.74379747.586362.27789767.216354.7696
9790.772347.07249821.941333.61689839.862328.38369884.492 317.8969915.446309.0359
9946.805302.63449960.318301.29249982.899300.614410000.82299.409410030.01300.6754
10064.46300.438710087.87301.919710101.73 303.987 10135.3305.101310140.85307.1956
10151.43309.281710157.28312.289210161.47313.088510190.81317.2659 10199.2317.6969
10207.58317.217110211.77 317.83510228.54325.212410266.27339.468910282.56343.6772
#Mann= 3 , 0 , 0
9717.409   0.045       09717.409   0.045       010282.56   0.045       0
#XS Ineff= 2 , 0
       0                               0
Bank Sta=9717.409,10282.56
Exp/Cntr=0.3,0.1

Type RM Length L Ch R = 1 ,6270.834,198.517300,198.517300,198.517300
XS GIS Cut Line= 6
1247069.80384112624516.7157865311246989.88013958624685.825624345
1246962.33802102624736.6225423751246914.35099017624813.977753783
1246889.26774868624858.3530716381246805.90507187625033.217756003
#Sta/Elev= 30
9709.718354.35979728.287346.94059760.946332.86529789.238322.84769804.492318.5796
 9840.78310.12339855.295306.16359866.019304.05939873.439303.78239889.054300.8882
9896.732 300.0669910.501297.28459921.292 296.2879944.917295.96399974.141 294.159
9989.541294.648310004.98293.845510032.07294.107310047.51293.072110070.12 292.792
10088.96293.0015 10107.5294.022710122.16297.281810140.49303.351610151.49307.6471
10158.82307.610910169.82306.859710172.65 307.46610242.15331.146510290.29343.7118
#Mann= 3 , 0 , 0
9709.718  0.0563       09709.718  0.0563       010290.29  0.0563       0
#XS Ineff= 2 , 0
       0                               0
Bank Sta=9709.718,10290.29
Exp/Cntr=0.3,0.1

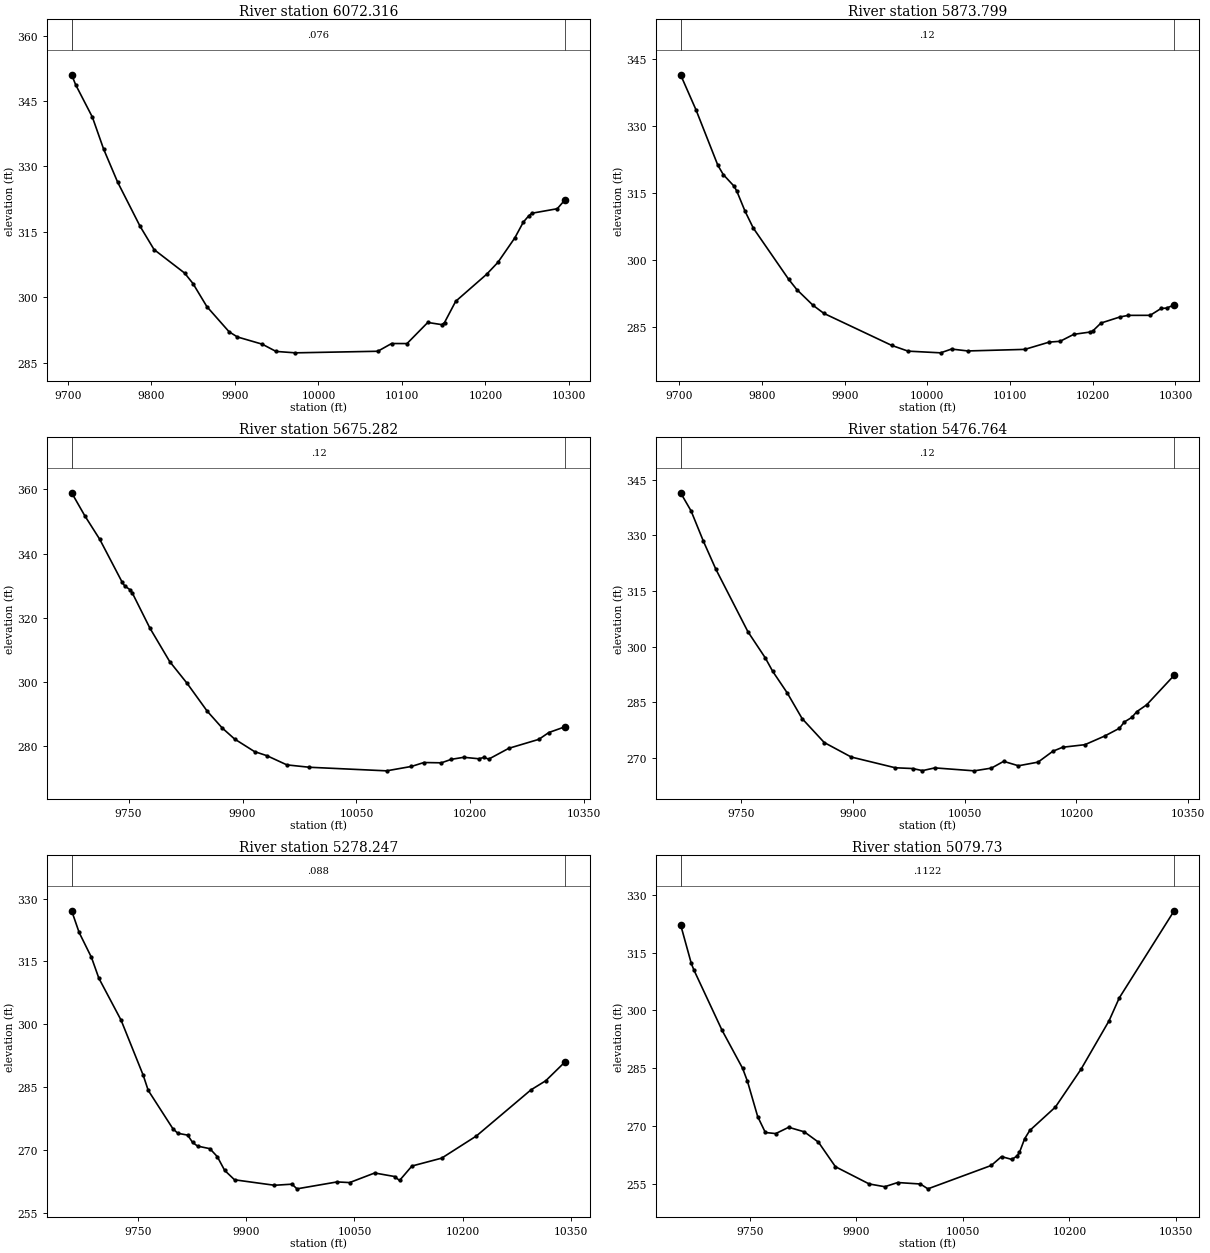
Type RM Length L Ch R = 1 ,6072.316,198.517300,198.517300,198.517300
XS GIS Cut Line= 6
1246800.85352126624417.3386963971246764.16994693624606.274014876
 1246751.2440857624754.3187271281246742.91323972624814.268537702
1246727.04058834624893.7929184191246700.08942286624998.794398724
#Sta/Elev= 30
9704.392351.02419709.115348.76439729.251341.29069742.675 333.9729759.455326.3936
9786.303316.27649803.083310.92269839.703305.5253 9849.69303.12639866.336297.8343
9892.968292.05649902.911290.86829932.651289.21139949.173287.5495 9972.25287.2239
10071.06287.585910087.62289.362110106.09  289.3510130.93294.194310147.66293.6975
   10151294.174910164.38299.048410201.36305.237510214.91 307.97310235.23313.6076
10245.39317.219510251.62318.604210255.55319.251610286.04320.289210295.59 322.396
#Mann= 3 , 0 , 0
9704.392   0.076       09704.392   0.076       010295.59   0.076       0
#XS Ineff= 2 , 0
       0                               0
Bank Sta=9704.392,10295.59
Exp/Cntr=0.3,0.1

Type RM Length L Ch R = 1 ,5873.799,198.517300,198.517300,198.517300
XS GIS Cut Line= 6
1246568.36691997624409.9126862221246554.91110668624591.454131862
1246557.53167412624768.0515344581246555.59386555624848.591832232
1246548.73742344624933.720133972 1246539.1110227625005.175387678
#Sta/Elev= 30
9701.592341.44369720.282333.57669746.649321.19679753.241319.10799766.424316.4827
 9769.72315.34439779.608310.88789789.495 307.1489832.225295.6929 9842.08 293.396
 9861.79289.8556 9874.93288.05079956.966280.88669976.662279.609410016.05 279.229
10029.18280.076410048.87279.651210117.79280.002410147.35281.631610160.51281.8123
10176.97283.365310196.72283.881610200.01284.121310209.89285.893710232.96287.2624
 10242.9287.613510269.38287.620910282.62289.157210289.24289.2463 10298.4289.9591
#Mann= 3 , 0 , 0
9701.592    0.12       09701.592    0.12       0 10298.4    0.12       0
#XS Ineff= 2 , 0
       0                               0
Bank Sta=9701.592,10298.4
Exp/Cntr=0.3,0.1

Type RM Length L Ch R = 1 ,5675.282,198.517300,198.517300,198.517300
XS GIS Cut Line= 6
1246373.26612121 624378.557577431246365.60059328624454.343813385
1246360.17153949624548.1363916761246354.06607976 624890.11749907
1246349.98517541624951.5078196821246341.92744185625027.421461203
#Sta/Elev= 30
9674.984358.93089692.224351.79979712.009344.42729741.687331.00619744.985329.8949
9751.579328.79959754.865327.74769777.869316.8703 9804.16306.36349827.164299.5665
9853.442290.9587 9873.13285.73989889.536282.27949915.786278.36049932.193277.0752
9958.443274.21869987.974 273.48110089.69272.3654 10122.5273.736710138.92274.9545
10161.89274.859310175.02275.948910191.44276.583210211.17276.125110217.75276.5406
10224.32276.016810250.64279.373410290.23282.165710303.42284.291510325.02286.1082
#Mann= 3 , 0 , 0
9674.984    0.12       09674.984    0.12       010325.02    0.12       0
#XS Ineff= 2 , 0
       0                               0
Bank Sta=9674.984,10325.02
Exp/Cntr=0.3,0.1

Type RM Length L Ch R = 1 ,5476.764,198.517200,198.517200,198.517200
XS GIS Cut Line= 6
1246197.98805411624385.0481950771246179.67306397 624509.03229651
1246166.23664851624672.7756452681246155.60624439624750.403779324
1246141.31319578624894.9904208041246118.62769961625042.268885706
#Sta/Elev= 30
9668.847341.5133 9682.94336.61219699.522328.40349716.105320.90449759.218303.9894
9782.433296.95239792.383293.32339812.172287.40319831.951280.53119861.613274.0748
9897.796270.16319957.003267.25689980.187267.05449993.442266.490110009.99267.2264
10062.85266.430510085.93267.166810102.41268.9959 10122.2267.796110148.57268.7843
10168.35271.715310181.54272.801710211.35273.488310237.85275.821610257.72277.9232
10264.35279.634810274.33280.854410280.99282.407610294.31284.261310331.17292.2277
#Mann= 3 , 0 , 0
9668.847    0.12       09668.847    0.12       010331.17    0.12       0
#XS Ineff= 2 , 0
       0                               0
Bank Sta=9668.847,10331.17
Exp/Cntr=0.3,0.1

Type RM Length L Ch R = 1 ,5278.247,198.517300,198.517300,198.517300
XS GIS Cut Line= 6
1246068.87073248624349.6737731691246001.41909097624576.220125529
1245967.03293881624675.533664378 1245966.2526408624677.375167843
1245937.56909762624758.8205240531245860.83853707625002.140643653
#Sta/Elev= 30
9657.527327.08499667.905321.90649685.021315.95749695.291310.98939726.099300.9924
9756.908287.81179763.754284.24649797.986275.09969804.832274.00449818.525273.5633
9825.371 271.8189832.217270.94729849.333270.33149859.603268.43899869.872265.1469
9883.565262.90769938.968261.59949963.272261.86299970.216260.749910025.86262.4012
10043.26262.242910078.04264.530510105.66263.688810112.54262.742410129.74266.1926
10171.02268.072910219.19273.361810294.87284.356310315.51286.543310342.48291.0814
#Mann= 3 , 0 , 0
9657.527   0.088       09657.527   0.088       010342.48   0.088       0
#XS Ineff= 2 , 0
       0                               0
Bank Sta=9657.527,10342.48
Exp/Cntr=0.3,0.1

Type RM Length L Ch R = 1 , 5079.73,198.517300,198.517300,198.517300
XS GIS Cut Line= 6
1245929.74278602624286.7845490061245880.32417738624397.310240739
1245800.69144753624559.557022155 1245760.7610775624656.985656225
1245694.66542154624800.5961199321245642.56275369624919.235166295
#Sta/Elev= 30
9652.622322.26359667.718312.19399671.312310.52699710.844294.92559739.955284.9923
9746.783281.62779761.158272.4881 9771.94268.36489786.529268.08299804.802269.7152
9826.731268.53939846.685265.85579870.587259.49139918.098255.01889940.026254.3028
9958.187255.38769990.123255.009210000.75253.753210089.93259.815510104.37262.1132
10118.82261.384310126.04262.241410129.65263.202110136.88266.7236 10144.1268.8818
10180.22  274.9610216.33284.779710255.76297.337610270.09303.250510347.39325.8579
#Mann= 3 , 0 , 0
9652.622  0.1122       09652.622  0.1122       010347.39  0.1122       0
#XS Ineff= 2 , 0
       0                               0
Bank Sta=9652.622,10347.39
Exp/Cntr=0.3,0.1

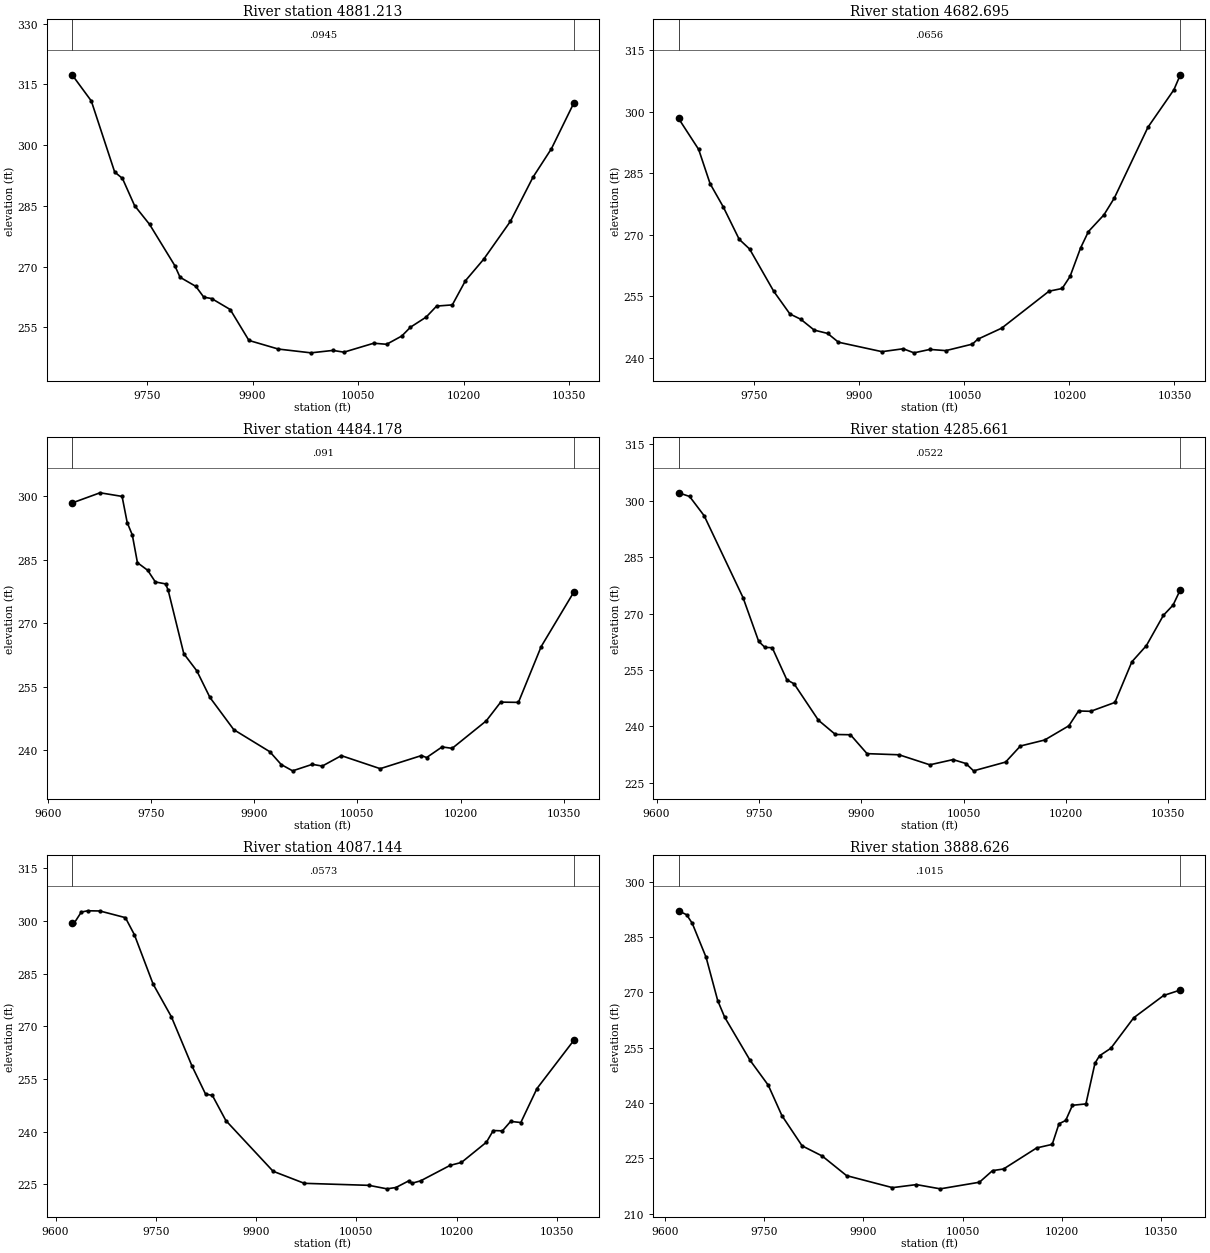
Type RM Length L Ch R = 1 ,4881.213,198.517300,198.517300,198.517300
XS GIS Cut Line= 6
1245796.89486776624177.852541419 1245695.7818614624368.127696965
1245645.68218762624453.9529152591245602.64966502624520.628387174
1245564.01434869624588.5813606541245453.26899139624801.920069607
#Sta/Elev= 30
9643.609317.3656 9670.92310.90569704.123293.35539715.191 291.7719732.374285.0723
9753.761280.4102 9789.52270.25179797.004267.36719819.458265.11719830.685262.4582
9841.912262.11239868.245259.40669894.837 251.7729936.625249.64399982.891248.7109
10014.15249.309310029.75248.875910072.14251.085510090.39 250.82110111.96252.8642
10124.23255.034210146.55257.534810161.42260.253610183.74260.549310202.32266.5009
10228.37 271.83810266.29281.186410298.29292.063510324.59299.128310356.39310.4121
#Mann= 3 , 0 , 0
9643.609  0.0945       09643.609  0.0945       010356.39  0.0945       0
#XS Ineff= 2 , 0
       0                               0
Bank Sta=9643.609,10356.39
Exp/Cntr=0.3,0.1

Type RM Length L Ch R = 1 ,4682.695,198.517300,198.517300,198.517300
XS GIS Cut Line= 6
1245622.92840203624110.5275491441245561.58752051624217.872805976
1245446.59419214624404.826711963 1245380.8124464624518.624055218
1245327.68416505624614.1810312081245266.50604613624731.994677272
#Sta/Elev= 30
9641.674 298.3249670.427290.7661 9686.73282.42729705.623276.73699728.296268.8652
9743.166266.49339777.653 256.1869800.764250.65839816.171249.3807 9835.43246.7314
9854.689245.91259870.096243.77599932.204241.47339962.538242.17899977.946241.1873
10000.69242.020510023.44 241.72710061.37243.315110068.96244.5013 10103.1 247.197
10170.81256.212310189.58256.873810200.84259.811510215.85266.735310227.09270.7526
10249.27274.828710264.06278.916110312.12296.189310349.15305.311110358.33308.9634
#Mann= 3 , 0 , 0
9641.674  0.0656       09641.674  0.0656       010358.33  0.0656       0
#XS Ineff= 2 , 0
       0                               0
Bank Sta=9641.674,10358.33
Exp/Cntr=0.3,0.1

Type RM Length L Ch R = 1 ,4484.178,198.517200,198.517200,198.517200
XS GIS Cut Line= 6
1245496.58808701623970.7245546341245368.47378275624197.735002048
1245331.09204394 624248.420137781245280.56205434 624299.94498265
1245257.30509604624334.0918519911245121.44995271624592.260503538
#Sta/Elev= 30
 9635.49298.40829676.161  300.82 9708.15299.96459715.589293.77549723.027290.8398
9730.466284.29629745.344282.49699756.502279.73529771.379279.28239775.098  277.79
9797.801262.78789816.781258.71859835.762 252.4429870.414244.8231 9922.74239.6141
9939.322236.58039955.904235.08939984.519236.6245    9999 236.21510026.68238.6813
10083.14235.602110143.07238.696710150.56238.229410173.03240.741410187.71 240.408
10237.26246.910110258.22251.331310283.96251.273610317.04264.4709 10364.5277.3626
#Mann= 3 , 0 , 0
 9635.49   0.091       0 9635.49   0.091       0 10364.5   0.091       0
#XS Ineff= 2 , 0
       0                               0
Bank Sta=9635.49,10364.5
Exp/Cntr=0.3,0.1

Type RM Length L Ch R = 1 ,4285.661,198.517300,198.517300,198.517300
XS GIS Cut Line= 6
1245267.33890829623888.6749628851245149.71674038624166.310996858
1245131.67913435624202.1210063121245093.35114387624267.959278948
1245059.59994038 624338.431911791244967.80482315624559.756190613
#Sta/Elev= 30
9632.219302.13789648.412301.1602 9669.79296.0276  9726.8274.24879749.665262.6434
9758.868261.02849769.558260.94669790.936252.43069801.626251.33989837.257241.6634
9862.199237.87159884.231237.80139908.519232.77799955.494232.473410000.58229.8073
10034.65231.193810053.44230.1525 10064.7228.205210111.64230.537610133.34234.8091
10168.86236.398210204.38240.184610218.59244.122310236.34244.031610271.86246.3894
10296.73257.194610318.04261.5085 10342.9 269.53710357.11272.268410367.77276.3506
#Mann= 3 , 0 , 0
9632.219  0.0522       09632.219  0.0522       010367.77  0.0522       0
#XS Ineff= 2 , 0
       0                               0
Bank Sta=9632.219,10367.77
Exp/Cntr=0.3,0.1

Type RM Length L Ch R = 1 ,4087.144,198.517300,198.517300,198.517300
XS GIS Cut Line= 6
 1245038.9024482623779.0173139571244980.26369648623960.198342111
1244959.43411641624047.2650350691244910.81206131624292.282388946
1244882.27617407624397.8432698231244847.92366241624504.009247332
#Sta/Elev= 30
9624.616299.51359627.979299.4972  9638.4302.57389647.955302.94839666.189302.8931
9704.398300.99139717.868296.1282 9745.83282.0858 9773.19272.7642 9803.97258.7636
9824.362250.72359834.483250.37549854.723 243.1969925.357228.76079972.114225.3225
10068.89224.745910095.74223.751810109.18224.131910128.46226.0381 10132.7225.3216
10146.14 226.03110190.22230.431810207.21231.2704 10244.6237.038610254.79240.3591
10268.46240.263110280.82242.955110296.04242.640910320.18 252.31510375.39266.0593
#Mann= 3 , 0 , 0
9624.616  0.0573       09624.616  0.0573       010375.39  0.0573       0
#XS Ineff= 2 , 0
       0                               0
Bank Sta=9624.616,10375.39
Exp/Cntr=0.3,0.1

Type RM Length L Ch R = 1 ,3888.626,198.517300,198.517300,198.517300
XS GIS Cut Line= 6
1244828.74596422623782.4045496971244763.77368752623980.840549569
1244748.58952562624069.8100093661244743.77011773624203.620978372
1244732.65425365624286.7880055831244664.32174348624517.965296464
#Sta/Elev= 30
9620.769292.14769632.973291.06829641.512288.75039662.479279.49619679.952267.8071
9690.436263.30589728.873251.60289756.379244.84819776.976236.61369807.516 228.404
9837.948225.63799874.759220.31979944.159217.06369980.285217.888410016.38216.7392
10075.57218.530210095.36221.677110111.98 222.11810162.08227.8331 10185.6228.7977
10195.79234.372510205.98 235.28510216.16239.393510236.54239.7728 10250.2250.7937
10257.07252.822510274.25254.864910308.78263.129410353.98 269.17410379.24270.6556
#Mann= 3 , 0 , 0
9620.769  0.1015       09620.769  0.1015       010379.24  0.1015       0
#XS Ineff= 2 , 0
       0                               0
Bank Sta=9620.769,10379.24
Exp/Cntr=0.3,0.1

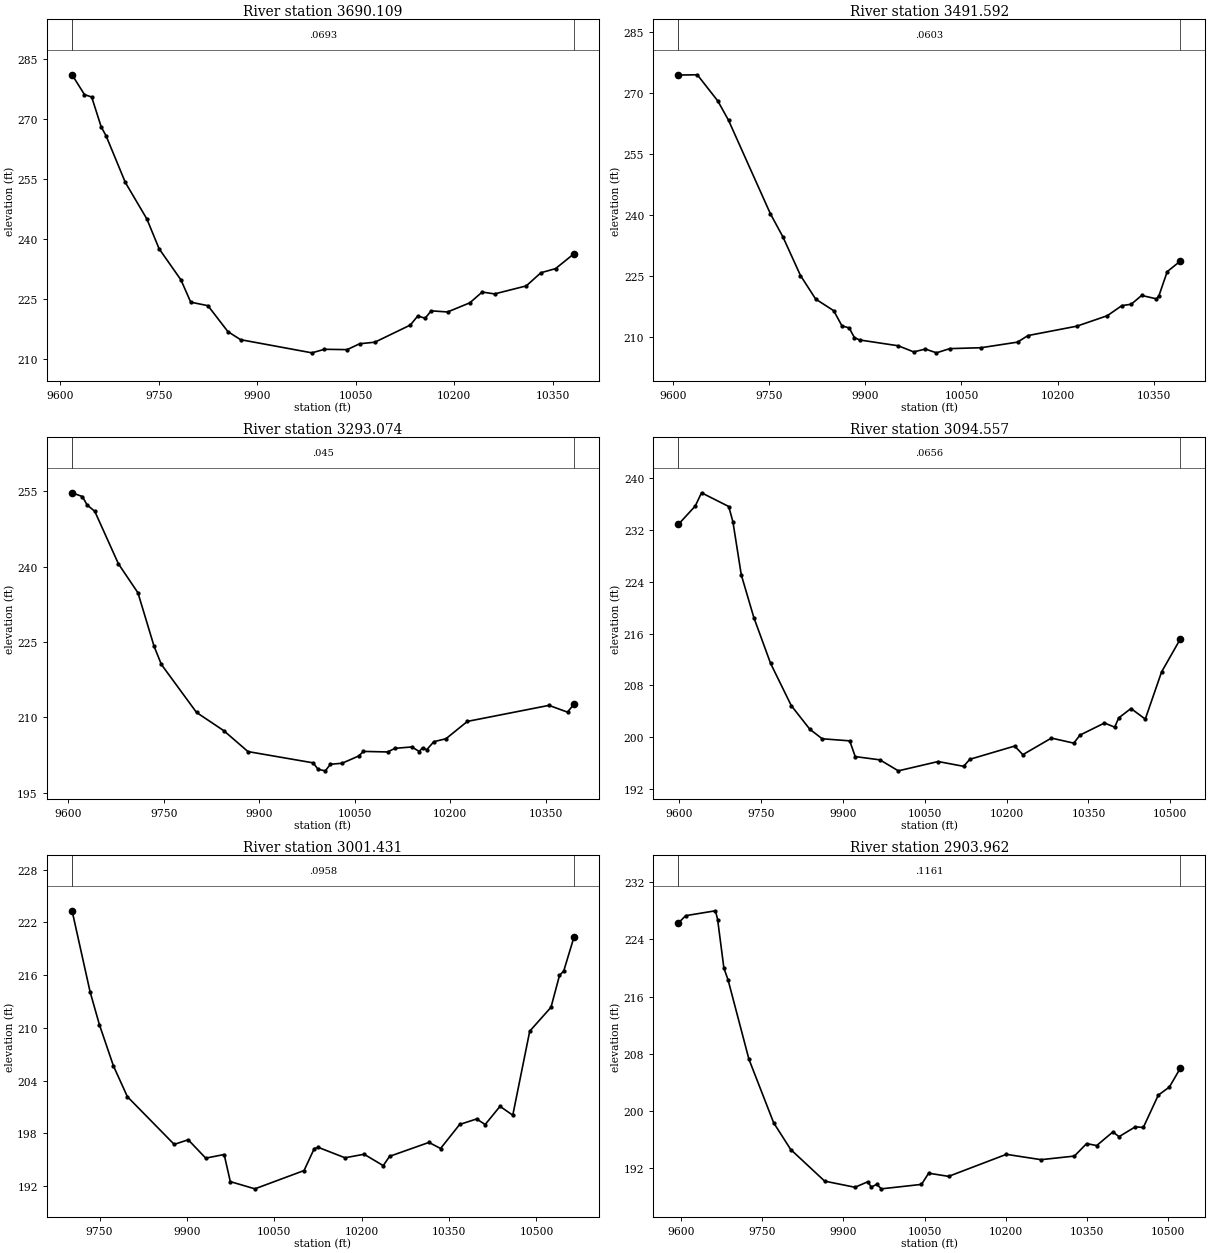
Type RM Length L Ch R = 1 ,3690.109,198.517300,198.517300,198.517300
XS GIS Cut Line= 6
1244748.73751487 623745.528964171244700.73784328623843.421539999
1244660.54044679623919.5366629671244477.76316096624218.030445818
1244430.11835196624302.2812758971244372.44075332624410.586727462
#Sta/Elev= 30
9617.684 280.9359636.595275.98819647.557275.38229662.173 267.8729669.481265.6968
9698.869254.03879731.674244.92249750.225237.51269783.618229.69779798.459224.1572
9824.703223.27099855.079216.80569874.427214.78499983.062211.498510002.23212.3825
10036.77212.300310055.96213.770410078.99214.153310133.12218.444410144.24220.6798
10155.75220.153110164.83221.9893 10189.8221.702710223.72223.991310242.57226.6852
10261.39226.210210309.71228.215610332.01 231.49710354.32232.524110382.32236.2302
#Mann= 3 , 0 , 0
9617.684  0.0693       09617.684  0.0693       010382.32  0.0693       0
#XS Ineff= 2 , 0
       0                               0
Bank Sta=9617.684,10382.32
Exp/Cntr=0.3,0.1

Type RM Length L Ch R = 1 ,3491.592,198.517200,198.517200,198.517200
XS GIS Cut Line= 6
1244639.46005436623613.3791503041244578.70682166623715.377184352
1244532.08653485623787.8373333171244307.62913401624099.820443537
1244262.40005104624168.041702105 1244203.5703788624263.314246495
#Sta/Elev= 30
9608.472274.42079637.876274.48639669.932268.02949686.583263.29069751.864240.3269
9771.532234.59889798.841225.13139822.533219.34069850.715216.47299863.502212.7697
9874.871212.22939882.923 209.8759890.975209.28619951.365207.85359975.521206.3494
9993.697207.0469   10011206.116510031.82207.1528 10080.6207.3757 10137.5208.7499
10153.76 210.36210230.03212.673410277.53215.240710300.35217.731410314.89218.0651
 10331.2  220.2310354.34219.387510358.19220.174610371.09226.079810391.53228.6771
#Mann= 3 , 0 , 0
9608.472  0.0603       09608.472  0.0603       010391.53  0.0603       0
#XS Ineff= 2 , 0
       0                               0
Bank Sta=9608.472,10391.53
Exp/Cntr=0.3,0.1

Type RM Length L Ch R = 1 ,3293.074,198.517300,198.517300,198.517300
XS GIS Cut Line= 6
1244456.65938578623512.5969680591244284.76135574623784.216855522
1244249.89047223623846.9584960421244248.92526277623848.710172584
1244214.45075284623911.6801969841244049.88079665624187.800127041
#Sta/Elev= 30
9605.775254.73239621.978253.9826 9629.51252.28979641.391251.0512 9678.59240.5811
9709.265234.80479734.575224.16589746.076220.53459801.291210.97479844.237207.3348
9882.116203.17799984.449200.93449992.467199.628610003.71199.3413 10011.6200.6533
 10029.9200.847510056.08 202.29710063.56203.214210101.56 203.10210113.02203.8217
10139.75204.102910151.21203.190210156.37203.947410162.78203.522510174.13 205.143
10193.22205.738910226.86209.189710355.03212.381910384.19211.034110394.23212.6234
#Mann= 3 , 0 , 0
9605.775   0.045       09605.775   0.045       010394.23   0.045       0
#XS Ineff= 2 , 0
       0                               0
Bank Sta=9605.775,10394.23
Exp/Cntr=0.3,0.1

Type RM Length L Ch R = 1 ,3094.557,93.126100,93.126100,93.126100
XS GIS Cut Line= 6
1244298.42863363623378.5900010171244207.90959272623528.297167167
1244114.21249738623691.7806961541244096.42826408623724.045798659
 1244034.5115194623837.1384514271243847.12498337 624179.75548771
#Sta/Elev= 30
9598.782232.84799629.525235.66159641.027237.70489690.868235.58919698.536233.2398
9713.872225.05339736.875218.47169767.547211.40669805.446204.89519839.479201.2445
9862.168199.77659912.612199.45599922.672197.03029967.994196.522510001.69 194.832
10074.65 196.267 10121.4 195.52510132.62196.609910214.89198.653410229.84 197.323
 10282.2199.881510323.33199.1003 10334.4200.335910379.42202.206410398.12201.5667
 10405.6202.995610428.04204.442710454.21202.807410484.13210.087910518.45215.1594
#Mann= 3 , 0 , 0
9598.782  0.0656       09598.782  0.0656       010518.45  0.0656       0
#XS Ineff= 2 , 0
       0                               0
Bank Sta=9598.782,10518.45
Exp/Cntr=0.3,0.1

Type RM Length L Ch R = 1 ,3001.431,97.468700,97.468700,97.468700
XS GIS Cut Line= 4
1244163.96526113623435.3978488151244040.26734444623611.179098815
 1243949.1215111 623847.724237711243777.68053892624201.456876591
#Sta/Elev= 30
 9702.73223.32619733.635214.11689749.682210.36619773.752205.6827 9797.68 202.186
9878.057196.75899902.128197.28739932.177 195.195 9963.82195.61029974.368192.5278
10016.56191.705410100.94193.783910118.52196.286110125.55196.419410171.27195.2368
10204.08  195.6410236.89194.346110247.83195.401510315.38196.985310335.33196.2927
10368.14199.027710397.31199.653410411.89199.016310437.41201.088910459.29200.0781
 10488.4209.635710524.91212.3516 10539.5215.969810546.79216.486310564.26220.3056
#Mann= 3 , 0 , 0
 9702.73  0.0958       0 9702.73  0.0958       010564.26  0.0958       0
#XS Ineff= 2 , 0
       0                               0
Bank Sta=9702.73,10564.26
Exp/Cntr=0.3,0.1

Type RM Length L Ch R = 1 ,2903.962,141.982300,141.982300,141.982300
XS GIS Cut Line= 6
1244079.82570595623301.9418762181243947.53306207623529.226088002
1243925.19325122623600.3427898291243900.07230997623769.089666039
1243873.00335401623855.0197697731243725.59720555624147.203404367
#Sta/Elev= 30
 9595.76226.29139609.052227.29979664.094227.98349668.026226.75589679.612219.9796
9687.322218.33029725.869207.24829771.487198.38069802.964194.65149865.666190.2351
9921.612189.37799945.158190.14639951.814189.40969961.799189.79039970.341 189.159
10044.39189.779310057.65191.342810094.43190.899510201.04 193.97610265.13193.2315
10326.72193.734810349.17195.476310367.87195.2032 10397.8197.108910409.03196.4396
10438.96197.810910453.93197.729510481.55202.239410502.03203.371110522.23206.0017
#Mann= 3 , 0 , 0
 9595.76  0.1161       0 9595.76  0.1161       010522.23  0.1161       0
#XS Ineff= 2 , 0
       0                 10082.6       0
Bank Sta=9595.76,10522.23
Exp/Cntr=0.3,0.1