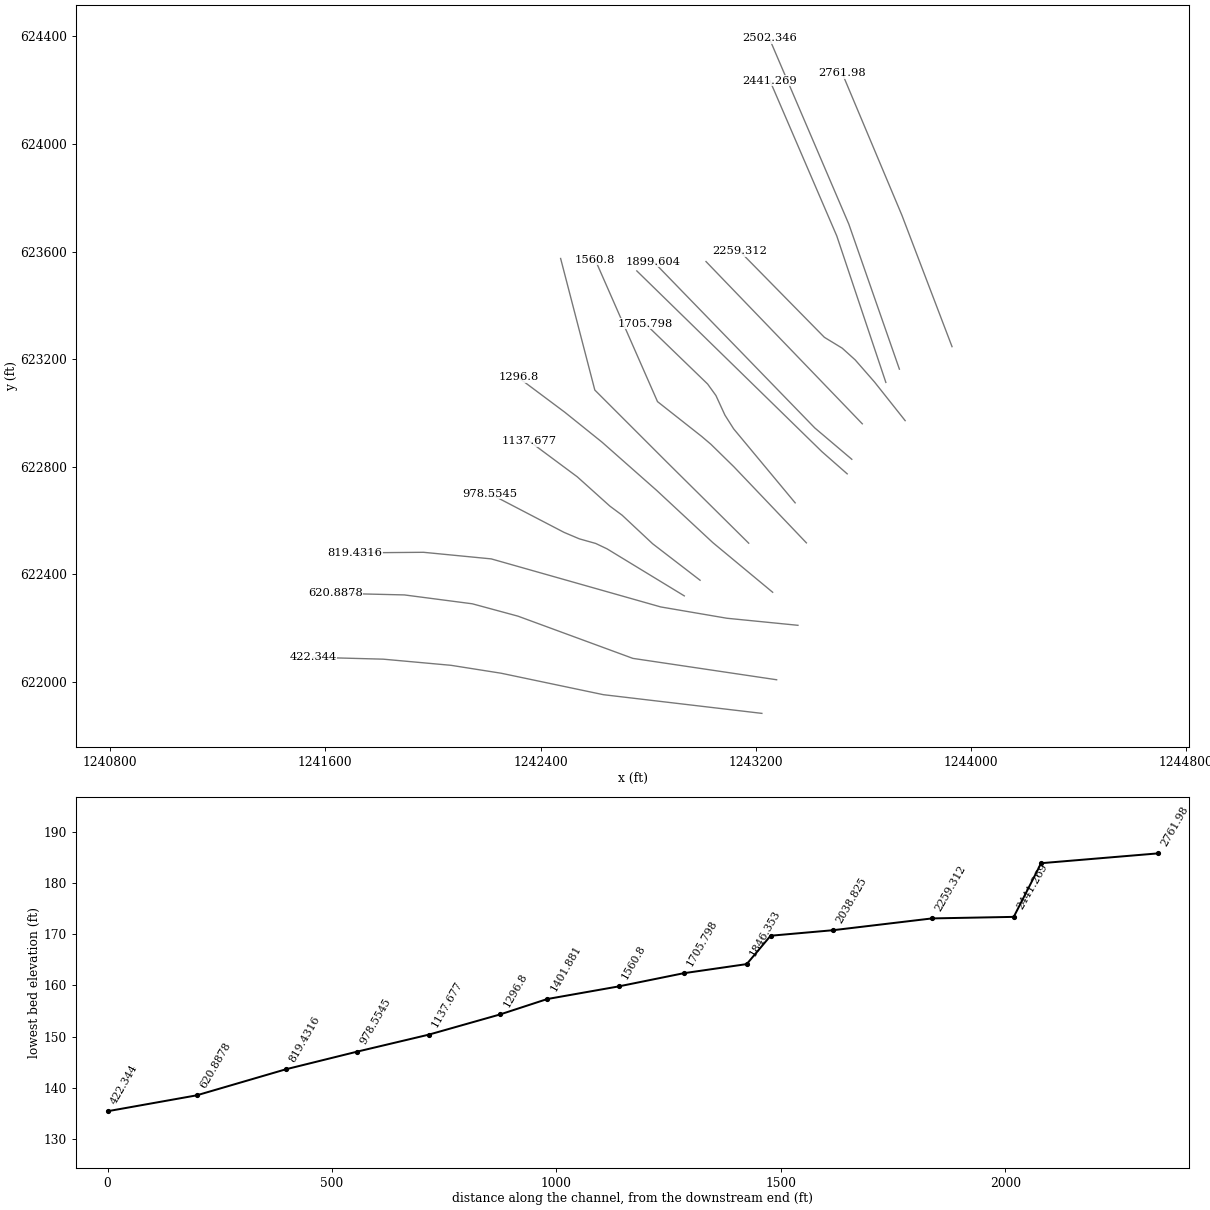
HEC-RAS study 400_ras.prj: 400

--- 400_ras.g01 (geometry) --- (continued)

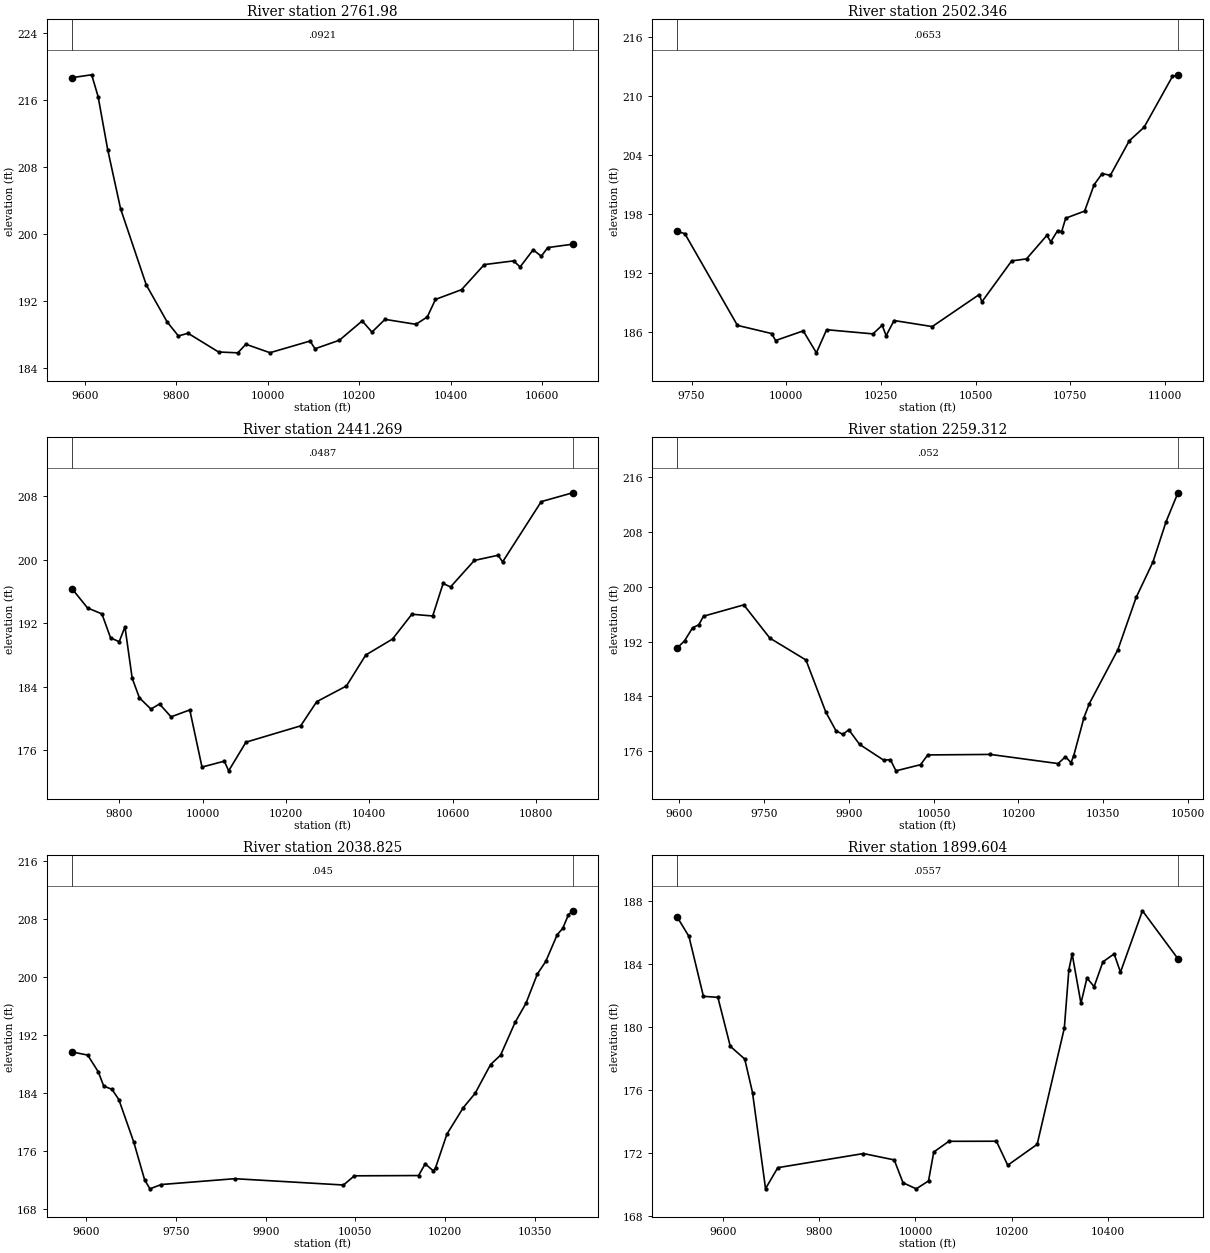
Type RM Length L Ch R = 1 , 2761.98,259.634200,259.634200,259.634200
XS GIS Cut Line= 3
1243929.55627701623246.637609914 1243743.5813618 623734.23570691
   1243521.60415624262.220765501
#Sta/Elev= 30
9572.165218.66499615.136219.00849629.181216.4088 9650.25210.04779678.341203.0109
9734.523193.9114 9780.17189.4912 9804.75 187.8179825.818188.14139892.534185.9041
9934.671185.80219952.228186.8281 10004.9185.817310092.68187.212910103.34186.2867
10156.73  187.3110206.55189.614610227.91188.278210256.38189.7996   10324 189.208
10348.91190.090610366.71192.181910423.65193.342610473.48196.340910537.54196.7827
10551.77196.057610580.25198.105710598.04197.340310612.28198.372110666.77198.7789
#Mann= 3 , 0 , 0
9572.165  0.0921       09572.165  0.0921       010666.77  0.0921       0
#XS Ineff= 2 , 0
       0 9824.09        10043.85       0
Bank Sta=9572.165,10666.77
Exp/Cntr=0.3,0.1

Type RM Length L Ch R = 1 ,2502.346,61.076300,61.076300,61.076300
XS GIS Cut Line= 3
1243733.90441502623163.0582951181243546.01661496623701.854192289
1243250.36963548624392.618162992
#Sta/Elev= 30
9712.293 196.2149732.142195.99579871.126186.67729961.465185.84849971.889185.1402
10044.86186.1181 10079.6183.889410106.59186.237310229.01185.813810253.33186.6909
10263.76185.628410284.65187.1708 10385.5186.556310509.48189.807110516.61189.0697
10595.13193.222210634.38193.428910687.91195.807210698.62195.172410716.46196.3006
10727.17196.199410737.87197.562910787.84198.279910812.82200.955910834.23202.0983
10855.64 201.907 10905.6205.412810944.86206.7963 11019.8211.962611034.28212.1229
#Mann= 3 , 0 , 0
9712.293  0.0653       09712.293  0.0653       011034.28  0.0653       0
#XS Ineff= 2 , 0
       09956.443        10184.16       0
Bank Sta=9712.293,11034.28
Exp/Cntr=0.3,0.1

Type RM Length L Ch R = 1 ,2441.269,181.957400,181.957400,181.957400
XS GIS Cut Line= 3
1243683.58179083623113.6858621541243501.22010258623658.007871076
1243252.54507315624235.486550599
#Sta/Elev= 30
9685.967196.35339723.203 193.9289757.804193.17489778.564190.15629799.324189.6705
9813.165191.54219830.465185.08179847.765182.60669875.446181.18419896.206181.8188
9923.887180.20019968.867181.07149998.218173.869310051.91174.612910062.29 173.394
10103.81177.005910235.29179.065210273.78182.111910345.23184.093210391.66 187.997
10455.96190.0091 10502.4193.134110552.41 192.91310577.41197.009810595.27196.5756
10652.43199.913810709.58200.5711 10720.3199.726910813.17207.328610888.77208.4441
#Mann= 3 , 0 , 0
9685.967  0.0487       09685.967  0.0487       010888.77  0.0487       0
#XS Ineff= 2 , 0
       09953.647        10180.22       0
Bank Sta=9685.967,10888.77
Exp/Cntr=0.3,0.1

Type RM Length L Ch R = 1 ,2259.312,220.487300,220.487300,220.487300
XS GIS Cut Line= 6
1243755.37273187622971.6093022691243641.20766572623115.467916446
1243569.55365763623197.4550902121243521.37743468623240.989344464
1243455.00308017623281.4214791081243139.88252426623601.966213064
#Sta/Elev= 30
9597.126191.0787 9609.97192.10499624.128194.01569635.101194.44999643.477195.7106
9714.681197.36549760.753192.50589824.559189.30449859.634181.68639877.405178.9849
9889.689178.41579900.202179.1063 9919.27176.96649961.796 174.6599973.715174.7233
9983.616173.0947   10027173.993510039.77175.420410150.39175.495310270.01174.1572
10283.12175.150410293.01 174.29810297.61 175.27310315.88180.891510325.22182.9155
10375.83190.826310408.03198.455410437.56203.602710460.96209.541810481.95213.7635
#Mann= 3 , 0 , 0
9597.126   0.052       09597.126   0.052       010481.95   0.052       0
#XS Ineff= 2 , 0
       09938.895        10202.07       0
Bank Sta=9597.126,10481.95
Exp/Cntr=0.3,0.1

Type RM Length L Ch R = 1 ,2038.825,139.221000,139.221000,139.221000
XS GIS Cut Line= 2
1243596.05168119622959.8486625551243015.15356377623562.876232103
#Sta/Elev= 30
9576.133189.68839602.402189.25019620.099 186.932 9629.21184.97129642.876184.5299
9654.421183.1178 9679.32177.26149697.542172.0382 9706.44170.78979725.356 171.384
 9848.31172.190110030.09171.318310048.31172.5868 10155.7172.625410166.75174.2393
10180.42 173.26410184.07173.6982 10203.2178.362110230.53182.005410250.28183.9755
10276.09187.950910292.84189.246110317.08193.763410335.31196.413610354.31 200.438
 10368.5202.200810387.42205.852510396.87206.760610406.33208.634910413.44209.1725
#Mann= 3 , 0 , 0
9576.133   0.045       09576.133   0.045       010413.44   0.045       0
#XS Ineff= 2 , 0
       09800.773        10064.47       0
Bank Sta=9576.133,10413.44
Exp/Cntr=0.3,0.1

Type RM Length L Ch R = 1 ,1899.604,53.250300,53.250300,53.250300
XS GIS Cut Line= 3
1243557.01257717622827.9658798461243419.44692826  622944.5024211
1242819.27665641623562.938744698
#Sta/Elev= 30
9504.257186.99399528.576185.76349558.674181.95519588.773181.88939614.572178.7771
9644.671 177.9639660.839175.83359687.967169.72189713.482171.05379891.782171.9522
9955.787 171.5479974.074170.095610001.51169.707110027.15170.209610038.08172.0521
10069.55172.730710168.48 172.73710192.04171.208610253.28172.539110309.81179.9348
10319.23183.6389 10326.1184.646510344.39181.514110356.92183.118410371.82182.5725
10390.11184.147310413.45184.655610426.68183.4895 10472.4 187.39710546.33184.3442
#Mann= 3 , 0 , 0
9504.257  0.0557       09504.257  0.0557       010546.33  0.0557       0
#XS Ineff= 2 , 0
       09807.371        10048.95       0
Bank Sta=9504.257,10546.33
Exp/Cntr=0.3,0.1

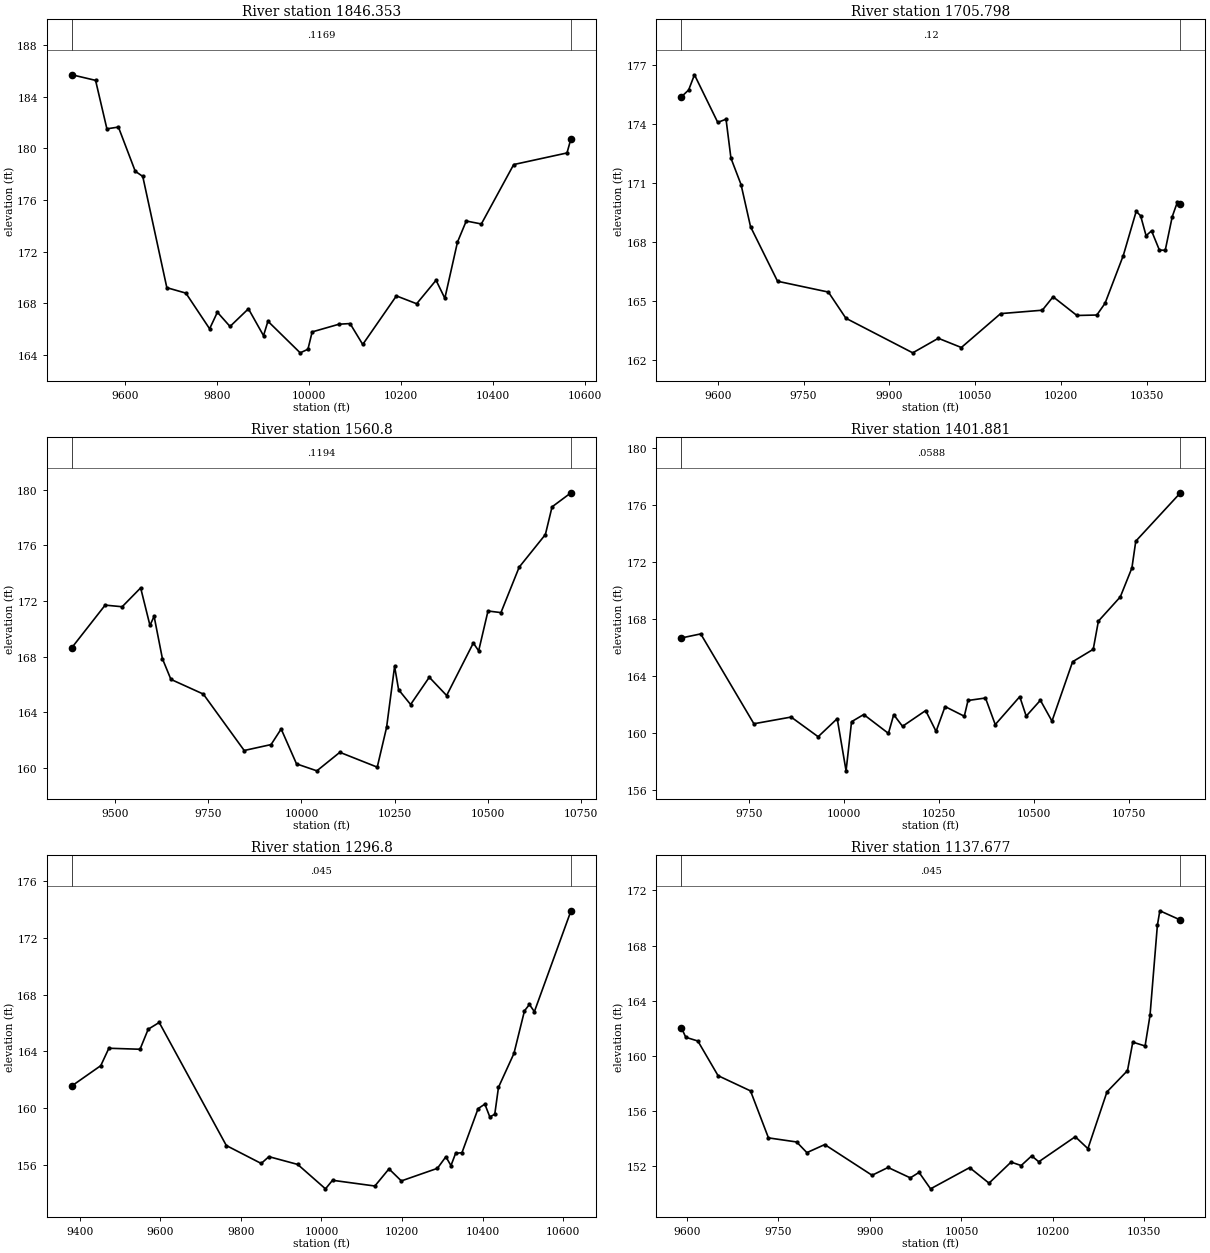
Type RM Length L Ch R = 1 ,1846.353,140.555800,140.555800,140.555800
XS GIS Cut Line= 3
1243539.90288493622773.8299885691243445.69924441622856.522004068
 1242757.9580701623528.144244581
#Sta/Elev= 30
9483.434185.68229534.907185.24999559.572181.49789584.639181.6358 9621.29178.2157
 9637.64177.81749690.076169.20589731.556168.7841 9783.21166.02329800.134167.3045
9827.649166.20249867.735167.57149900.605165.49039910.192166.60949980.434164.1622
9997.322164.440910006.49165.782510064.96166.377910089.04166.427710116.61164.8102
10189.92168.569610234.01167.961810276.27169.7801 10295.4 168.38410322.91172.7328
10342.01174.365110374.88174.135610445.32178.733910561.37179.632110570.07180.7476
#Mann= 3 , 0 , 0
9483.434  0.1169       09483.434  0.1169       010570.07  0.1169       0
#XS Ineff= 2 , 0
       0 9816.63        10069.39       0
Bank Sta=9483.434,10570.07
Exp/Cntr=0.3,0.1

Type RM Length L Ch R = 1 ,1705.798,144.997400,144.997400,144.997400
XS GIS Cut Line= 6
1243346.48897317622666.0708091411243117.85022411622941.091469392
1243085.45003998622992.1703414321243052.07975933623064.888644204
1243021.11969534623107.7288050951242789.83769736623331.315330178
#Sta/Elev= 30
9536.255 175.3739548.923175.72059559.106176.49179599.839174.07469614.316174.2382
9622.896172.26079640.572 170.9199657.218168.77719704.411166.01219793.319165.4629
9823.951164.13439940.895162.37839985.626163.117110025.89162.648910094.57 164.369
10167.53 164.54210186.35165.2237   10228164.274510262.89164.297710277.24164.8934
10309.15167.318210331.69169.557310339.43169.3371   10349168.325110358.56  168.57
10372.26167.596710382.48167.5809 10394.8169.294110403.82170.033110409.14169.9478
#Mann= 3 , 0 , 0
9536.255    0.12       09536.255    0.12       010409.14    0.12       0
#XS Ineff= 2 , 0
       0                10115.22       0
Bank Sta=9536.255,10409.14
Exp/Cntr=0.3,0.1

Type RM Length L Ch R = 1 ,  1560.8,158.918900,158.918900,158.918900
XS GIS Cut Line= 6
1243388.28867513622517.298811495 1243118.8259888622800.038089395
1243033.29293406622883.7940081661242998.41267738622913.435409069
1242834.82904604623042.3209111241242603.22694063623569.590082854
#Sta/Elev= 30
9383.598  168.659472.833171.69799518.483171.58129568.144172.93459593.153170.2384
9604.261170.89499626.586167.84999649.407166.36479736.434 165.3099846.218161.2571
 9918.38161.68259945.462162.80389986.709160.297110041.36159.796410103.08161.1273
10203.52160.0614 10228.6162.9179 10250.1167.300410260.85 165.624 10293.1164.5595
10343.27 166.51910389.86 165.20610461.52168.976210475.86168.414910500.94171.2754
10535.71171.160210584.66174.424110655.03176.765910672.94178.753710723.82179.7658
#Mann= 3 , 0 , 0
9383.598  0.1194       09383.598  0.1194       010723.82  0.1194       0
#XS Ineff= 2 , 0
       0                10149.53       0
Bank Sta=9383.598,10723.82
Exp/Cntr=0.3,0.1

Type RM Length L Ch R = 1 ,1401.881,105.081100,105.081100,105.081100
XS GIS Cut Line= 4
1243173.77922671622516.1312686661242869.84307958622817.304359913
1242601.82665898623085.3207805461242474.72608833623574.381671817
#Sta/Elev= 30
9572.358166.66699623.149166.95219762.983160.63979860.866161.1107 9931.91159.7294
9982.056160.999110005.34157.332810019.76160.784510051.74161.288710116.69159.9642
10130.61161.276510153.81 160.46110214.63161.567310241.97160.105810265.66161.8478
 10316.2161.168410325.98162.274410371.88162.4494 10397.6160.581310462.01162.5441
10478.96161.176310516.25162.289510546.75160.825510600.99164.996710655.23165.8701
10668.79167.848810726.41169.552510756.92171.585410767.09173.465810884.58176.8651
#Mann= 3 , 0 , 0
9572.358  0.0588       09572.358  0.0588       010884.58  0.0588       0
#XS Ineff= 2 , 0
       0                10199.64       0
Bank Sta=9572.358,10884.58
Exp/Cntr=0.3,0.1

Type RM Length L Ch R = 1 ,  1296.8,159.122900,159.122900,159.122900
XS GIS Cut Line= 6
1243262.85115009622333.7023293771243040.52259845622518.151345865
1242831.99769861622712.0528852181242628.40424246622891.811071821
1242490.03801954623003.0220507641242317.38110933623132.006112658
#Sta/Elev= 30
9380.835161.57759452.382162.99999472.467164.22719549.831164.15669570.053165.5677
9597.427166.04389763.929157.3716 9850.48156.1071 9869.55156.58789941.063156.0386
10009.94154.319110027.45154.9218 10132.5 154.51810167.52155.725810198.16 154.877
10287.62155.763810308.67156.5794 10321.3155.955910332.88 156.82310348.59156.8654
10388.64 159.97310405.43160.290510417.72159.3851   10430159.575910439.21161.4732
10477.59163.860810503.72166.863410515.96167.311610528.29 166.80510619.14173.9151
#Mann= 3 , 0 , 0
9380.835   0.045       09380.835   0.045       010619.14   0.045       0
#XS Ineff= 2 , 0
       0                10205.94       0
Bank Sta=9380.835,10619.14
Exp/Cntr=0.3,0.1

Type RM Length L Ch R = 1 ,1137.677,159.122900,159.122900,159.122900
XS GIS Cut Line= 6
1242993.05353698622378.3944817131242816.87514119622513.906112923
1242703.39726146622620.0757074591242658.10739681622653.671266101
1242536.72643481622762.7256680191242359.38264289622894.391805109
#Sta/Elev= 30
9590.845162.03649598.024161.34939617.806 161.0799650.963158.56719704.163157.4628
9733.576 154.0579779.797  153.769796.605152.98769825.877153.57179903.483151.3462
9929.694151.91259966.184151.15799980.531151.55459999.411150.362710063.44 151.902
10095.25150.775110131.38152.301410147.97152.051610165.24152.753910176.81152.3244
10236.67154.141610257.41 153.27610288.66157.391710322.31158.933610330.99160.9978
10351.15160.718610359.22162.931910371.32169.468510375.35  170.5210409.16169.8483
#Mann= 3 , 0 , 0
9590.845   0.045       09590.845   0.045       010409.16   0.045       0
#XS Ineff= 2 , 0
       0                               0
Bank Sta=9590.845,10409.16
Exp/Cntr=0.3,0.1

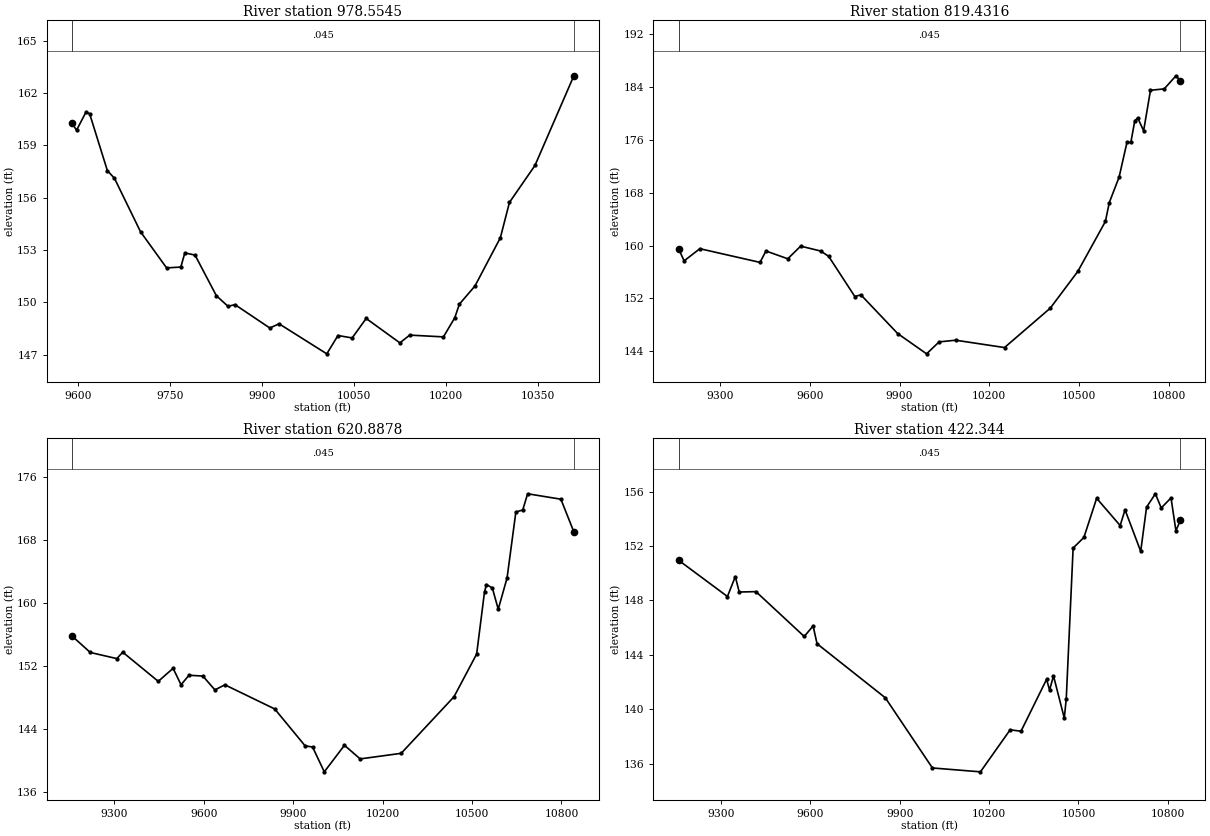
Type RM Length L Ch R = 1 ,978.5545,159.122900,159.122900,159.122900
XS GIS Cut Line= 6
1242934.43899256622320.2299912191242647.13949042622495.172338324
1242605.02706551622515.1416387321242544.34573143622532.252623915
 1242487.4668498622556.3108627061242212.12311277 622699.73617846
#Sta/Elev= 30
9590.851160.26079598.172159.87159613.627160.91529619.469160.81599648.401157.5561
9659.993157.11259702.494 154.0499744.996151.97799768.179152.02519774.755152.8374
9791.362152.71219826.136150.38529845.149149.77369856.514149.8724 9913.34148.5315
9928.443148.772610006.25147.050910024.47148.101910047.59147.961610070.46149.0789
10125.42147.679510141.45148.124610196.49148.022910214.98149.121510222.41149.8957
10247.85150.939210289.28 153.70310304.14155.733710345.75157.850210409.16162.9909
#Mann= 3 , 0 , 0
9590.851   0.045       09590.851   0.045       010409.16   0.045       0
#XS Ineff= 2 , 0
       0                               0
Bank Sta=9590.851,10409.16
Exp/Cntr=0.3,0.1

Type RM Length L Ch R = 1 ,819.4316,198.543800,198.543800,198.543800
XS GIS Cut Line= 6
1243356.93018433622210.8647017721243092.81016418 622237.10732366
1242847.08597262622279.1098327471242216.91855438622457.745254263
1241965.07360299622482.2481237631241709.63002077622480.146185786
#Sta/Elev= 30
9160.407159.52749179.081157.68159231.771159.52449433.044157.44939452.954159.1745
 9525.96157.99669569.105159.91299635.978159.17079662.727158.37019750.368 152.279
 9770.62152.53159893.657146.67049990.529143.594910032.27145.4041 10087.7145.6603
10251.22144.546610404.37150.516310496.74156.097810588.77163.646810601.89166.5064
10634.71170.374810660.95175.622310674.08175.6437 10687.2178.919610697.05179.3254
10716.74 177.39110739.71183.527510785.65183.735510825.04185.722610839.57184.9648
#Mann= 3 , 0 , 0
9160.407   0.045       09160.407   0.045       010839.57   0.045       0
#XS Ineff= 2 , 0
       0                               0
Bank Sta=9160.407,10839.57
Exp/Cntr=0.3,0.1

Type RM Length L Ch R = 1 ,620.8878,198.543800,198.543800,198.543800
XS GIS Cut Line= 6
1243277.70377827622008.4866296321242743.28951794622087.947500961
1242316.04276545622244.9338930721242146.26544933622290.870609227
1241894.06152024622323.8064402041241637.95459826622329.908931567
#Sta/Elev= 30
9158.381155.79549219.451153.70829308.488152.92589328.344 153.7439447.483  150.03
9497.275151.68789523.913149.59499550.552150.80769597.169150.70279637.439148.9441
9671.024149.58729838.154146.51419940.166141.81319965.172141.665310004.45138.5061
10072.11141.887410124.79 140.15310262.31140.863310439.56148.0691 10515.5153.5056
10541.89161.423610548.47162.362410568.21161.915110587.95159.213610617.51163.1882
10647.07171.599110670.06171.849510686.48173.915710798.05173.2272 10841.6169.0618
#Mann= 3 , 0 , 0
9158.381   0.045       09158.381   0.045       0 10841.6   0.045       0
#XS Ineff= 2 , 0
       0                               0
Bank Sta=9158.381,10841.6
Exp/Cntr=0.3,0.1

Type RM Length L Ch R = 1 , 422.344,0.000000,0.000000,0.000000
XS GIS Cut Line= 6
1243222.79598359621883.5343501421242633.71566527621952.994340761
1242253.55116926622032.783705076 1242067.2575844 622062.17761837
1241815.57204602622085.0102268961241555.12425042622092.038398186
#Sta/Elev= 30
9158.091150.96269322.183 148.2939348.582149.75679361.781148.62279417.878148.6514
9579.866145.35469609.634146.12589622.889144.82079852.047140.843210010.01135.6841
10171.15135.398910270.85 138.489 10307.3138.385610393.22 142.20410403.12141.4091
10416.32142.456510452.58139.347710459.16140.779610482.19 151.85610518.39152.6391
10561.16155.515810640.01 153.51210656.43154.667410708.96151.613810728.65154.8646
10758.18155.847610777.87154.804510810.68155.543810827.08153.131910841.92153.8843
#Mann= 3 , 0 , 0
9158.091   0.045       09158.091   0.045       010841.92   0.045       0
#XS Ineff= 2 , 0
       0                               0
Bank Sta=9158.091,10841.92
Exp/Cntr=0.3,0.1